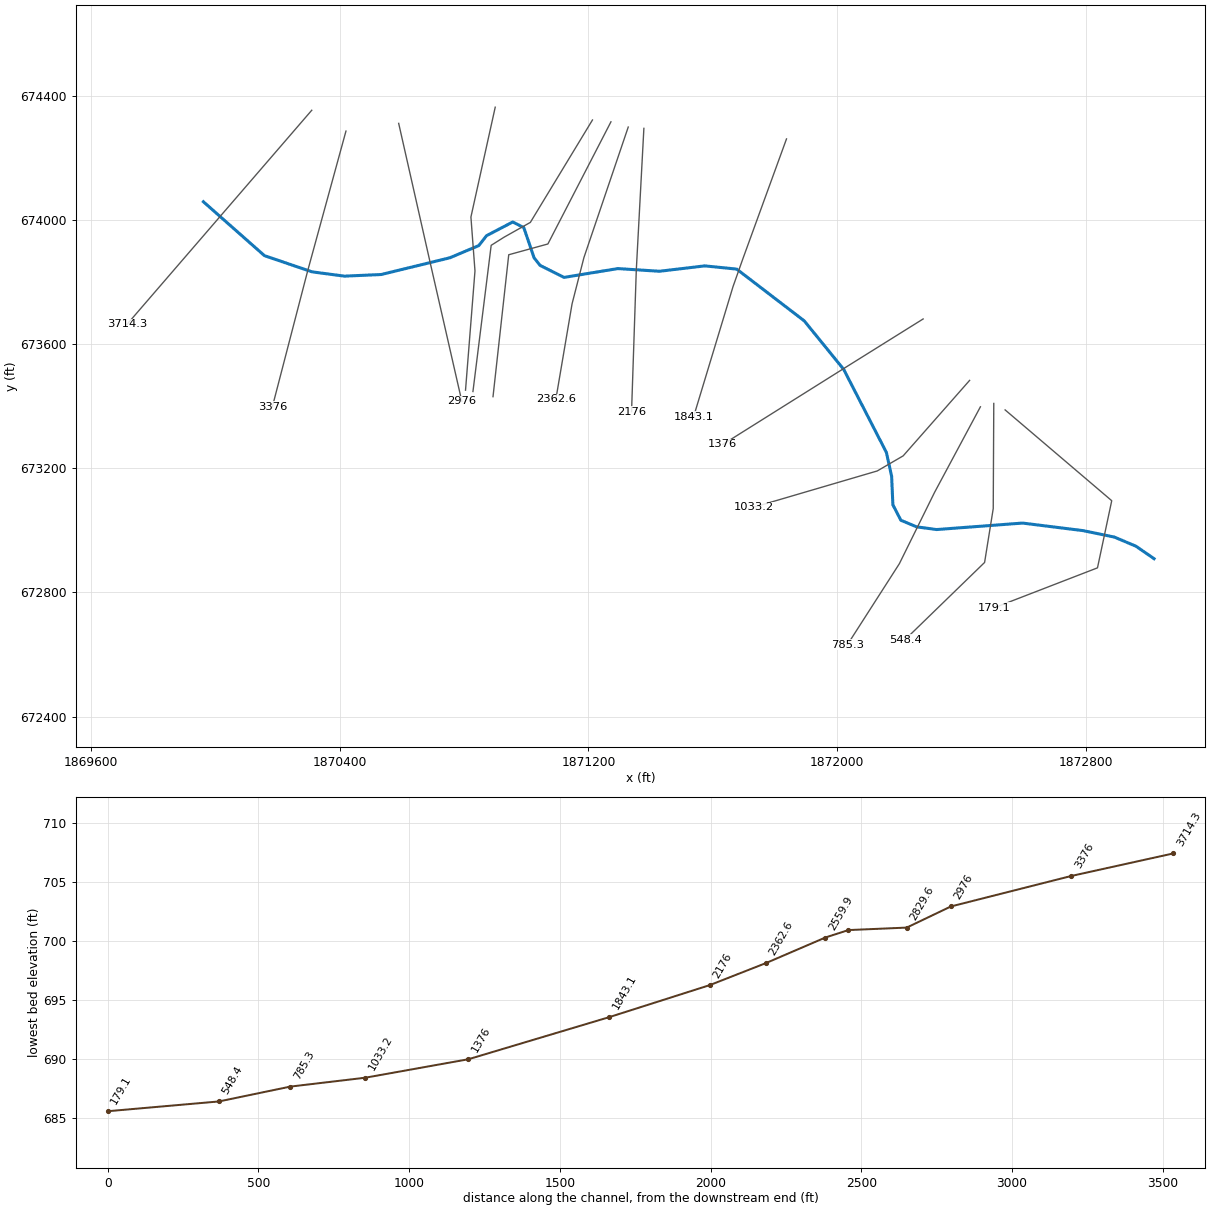
--- IslandRun.prj (project) ---

Proj Title=IslandRun
Current Plan=p01
Default Exp/Contr=0,0
English Units
Geom File=g01
Flow File=f01
Plan File=p01
BEGIN DESCRIPTION:
AMEC Environment & Infrastructure, 2013
Projection: NAD 1983 State Plane West Virginia South FIPS 4702 (US Feet)
Vertical Datum: NAVD 1988
END DESCRIPTION:
DSS Export Rating Curves= 0
DSS Export Rating Curve Sorted= 0
DSS Export Volume Flow Curves= 0
DXF OffsetX= 0
DXF OffsetY= 0
DXF ScaleX= 0
DXF ScaleY= 0

--- IslandRun.p01 (plan) ---

Plan Title=Floodplain
Program Version=4.00
Geom File=g01
Flow File=f01
K Sum by GR=0
Std Step Tol=0.01
Critical Tol=0.01
Num of Std Step Trials=20
Max Error Tol=0.3
Flow Tol Ratio=0.001
Split Flow NTrial=30
Split Flow Tol=0.02
Split Flow Ratio=0.02
Log Output Level=0
Friction Slope Method=1
Unsteady Friction Slope Method=2
Unsteady Bridges Friction Slope Method=1
Global Log Level=0
CheckData=False
Run HTab=0
Run UNet=0
Run PostProcess=0
UNET Theta=0
UNET Theta Warmup=0
UNET ZTol=0
UNET ZSATol=0
UNET MxIter=0
UNET MaxInSteps=0
UNET DtIC=0
UNET DtMin=0
UNET MaxCRTS=0
UNET WFStab=0
UNET SFStab=0
UNET WFX=0
UNET SFX=0
UNET DSS MLevel=0
UNET DZMax Abort=0
UNET Convert EG Bridges=0
UNET Use Existing IB Tables=0
UNET Froude Limit=0
UNET Froude Power=0
Write IC File=0
Echo Input=False
Echo Output=False
Write Detailed=0

--- IslandRun.f01 (steady flow) ---

Flow Title=NFF Regression Equation
Program Version=4.10
Number of Profiles= 1
Profile Names=P100yr
River Rch & RM=IslandRun,Main            ,3714.3
879.6814
River Rch & RM=IslandRun,Main            ,2362.6
936.0025
River Rch & RM=IslandRun,Main            ,179.1
962.1133
Boundary for River Rch & Prof#=IslandRun,Main            , 1
Up Type= 0
Dn Type= 3
Dn Slope=0.00241
DSS Import GetInterval= 0
DSS Import GetPeak= 0
DSS Import FillOption= 0

--- IslandRun.g01 (geometry) ---

Geom Title=USGS 3m DEM
Program Version=4.10

River Reach=IslandRun       ,Main
Reach XY= 30
     1869962.363      674058.221     1870158.628      673884.555
     1870311.468      673832.459     1870415.675      673818.571
     1870533.775      673823.788     1870754.343       673877.64
     1870847.641      673916.985      1870872.44      673948.854
     1870956.677      673992.974     1870992.276      673974.912
      1871025.28      673877.655     1871044.385      673853.341
     1871121.747      673814.534     1871294.481      673842.934
     1871428.214      673834.257     1871574.102      673851.633
     1871676.572      673841.218     1871893.678      673674.499
     1872020.471      673518.196     1872157.691       673250.74
     1872174.488      673174.192     1872178.541      673082.037
     1872204.161      673032.343     1872254.963       673011.07
     1872319.224       673002.39      1872595.37      673023.246
      1872789.89      672998.941     1872890.624      672978.105
     1872960.097      672948.584     1873018.036      672908.508

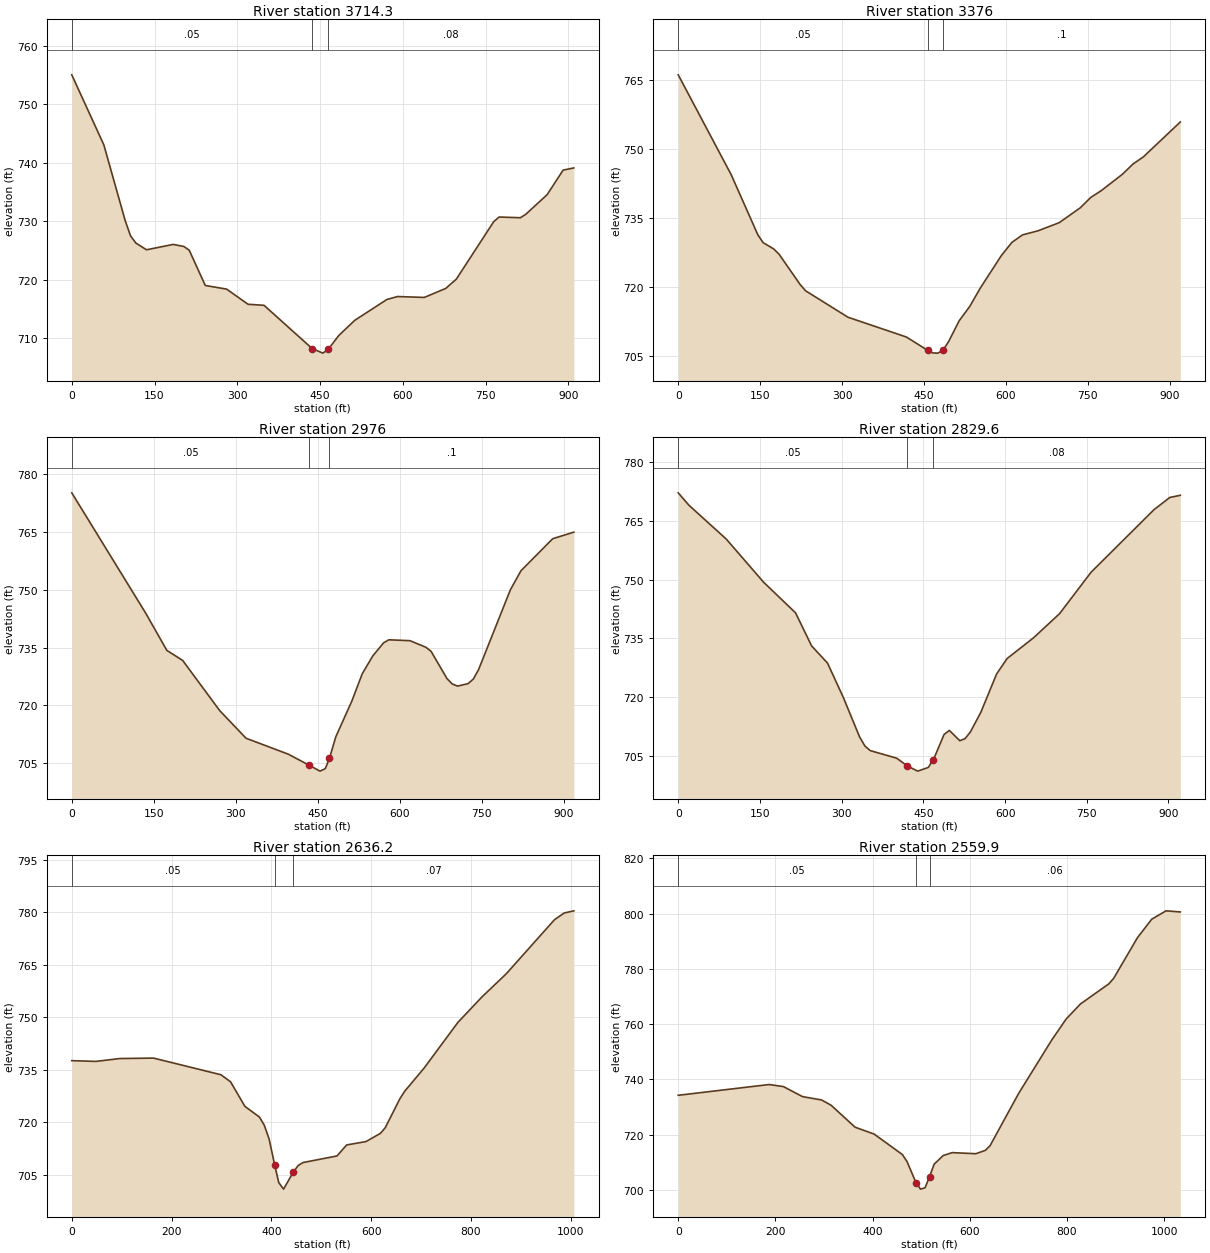
Type RM Length L Ch R = 1 ,3714.3  ,328.2,338.3,348.6
XS GIS Cut Line= 3
     1870310.668      674352.883     1870013.788      674008.082
     1869716.909      673663.281
#Sta/Elev= 30
       0  755.01    58.1  743.05    96.8  730.11   106.5  727.49   116.2  726.26
   135.5  725.11   183.9  726.03   203.3  725.67     213  725.02     242  719.01
   280.7  718.39   319.5   715.8   348.5  715.62   435.6  708.24     455  707.45
   464.7  708.08     484  710.47   513.1  713.07   571.2  716.62   590.5  717.12
   638.9  716.97   677.7   718.5     697  720.09   764.8  729.92   774.5  730.71
   813.2  730.59   822.9  731.18   861.6  734.53   890.6  738.73     910   739.1
#Mann= 3 , 0 , 0
       0     .05       0   435.6    .045       0   464.7     .08       0
Bank Sta=435.6,464.7
XS Rating Curve= 0 ,0
Exp/Cntr=0.3,0.1

Type RM Length L Ch R = 1 ,3376    ,389,400,410.8
XS GIS Cut Line= 3
     1870420.646      674285.733     1870297.681      673836.033
     1870184.014      673397.503
#Sta/Elev= 30
       0   766.1    97.1  744.33   145.7   731.3   155.4  729.59   174.8  728.21
   184.5  727.08   223.4  720.44   233.1  719.11   310.8  713.35   417.6  709.05
   456.5  706.16   466.2  705.58   475.8  705.54   485.5  706.31   495.1  708.07
   514.4  712.59   533.7   715.7     553  719.69   591.5  726.76   610.8  729.63
   630.1  731.26     659  732.17   697.5  733.93   736.1  737.17   755.4  739.43
   774.6  740.91   813.2  744.46   832.5  746.68   851.8  748.27   919.2  755.84
#Mann= 3 , 0 , 0
       0     .05       0   456.5    .045       0   485.5      .1       0
Bank Sta=456.5,485.5
XS Rating Curve= 0 ,0
Exp/Cntr=0.3,0.1

Type RM Length L Ch R = 1 ,2976    ,150.3,146.4,142.5
XS GIS Cut Line= 3
     1870590.078      674310.645      1870692.19      673858.236
     1870793.131      673414.962
#Sta/Elev= 30
       0  775.15   135.3  743.92   173.9  734.28   202.9  731.66   270.5  718.67
   318.8  711.48   396.2  707.34   434.8  704.44   454.1  702.95   463.8   703.6
   471.3  706.24   483.1   711.9   512.2  721.08   531.5  728.26   550.8  732.87
   570.2  736.21   579.9  737.02   618.6  736.79   647.6   735.1   657.2  734.05
   686.3  726.97   695.9  725.57   705.6  725.01     725  725.65   734.6  726.85
   744.3  729.33   802.3  749.99   821.7  754.94   879.7  763.24   918.4  764.95
#Mann= 3 , 0 , 0
       0     .05       0   434.8    .045       0   471.3      .1       0
Bank Sta=434.8,471.3
XS Rating Curve= 0 ,0
Exp/Cntr=0.3,0.1

Type RM Length L Ch R = 1 ,2829.6  ,218.8,193.4,166.8
XS GIS Cut Line= 4
     1870900.408      674362.728     1870822.283      674008.996
     1870835.304      673835.384     1870804.922       673451.27
#Sta/Elev= 30
       0  772.11    19.6  768.95    88.1  760.33   156.6  749.34   215.4  741.51
   244.8  733.09   274.1   728.7   303.5  719.81   332.9  709.88   342.7  707.56
   352.5  706.39     401  704.46   420.3   702.5   439.6  701.16     459   702.1
   468.6  704.11     488   710.5   497.7  711.54     517  708.91   526.7  709.46
   536.4  711.16   555.6  716.19   584.5  725.94   603.8  729.87     652  735.12
   700.1  741.31   757.9  751.87   873.5  767.83   902.4  770.93   921.7  771.48
#Mann= 3 , 0 , 0
       0     .05       0   420.3    .045       0   468.6     .08       0
Bank Sta=420.3,468.6
XS Rating Curve= 0 ,0
Exp/Cntr=0.3,0.1

Type RM Length L Ch R = 1 ,2636.2  ,81.5,76.3,71
XS GIS Cut Line= 5
     1871212.908      674321.496     1871013.256      673991.634
      1870928.62      673943.891     1870887.387       673917.85
     1870828.794       673446.93
#Sta/Elev= 30
       0  737.61    48.2   737.4    96.4  738.22   163.9  738.34   298.8   733.6
   318.1   731.6     347  724.56   375.9  721.54   385.6  719.25   395.3  715.35
   406.6  707.88   414.7  702.84   424.4  700.95   443.9  705.81   453.6  707.68
   463.3  708.53   531.5  710.42   550.9  713.56   589.6  714.52   618.7  716.88
   628.4  718.53   657.4  726.71   667.1  728.88   705.8  735.45   773.6   748.5
   822.1  755.82   870.5  762.38   967.3  777.83   986.7  779.75  1006.1  780.37
#Mann= 3 , 0 , 0
       0     .05       0   406.6    .045       0   443.9     .07       0
Bank Sta=406.6,443.9
XS Rating Curve= 0 ,0
Exp/Cntr=0.3,0.1

Type RM Length L Ch R = 1 ,2559.9  ,173.6,197.3,221
XS GIS Cut Line= 4
     1871272.364      674315.631     1871069.679       673922.19
     1870943.811      673887.468     1870893.291      673430.326
#Sta/Elev= 30
       0  734.26   186.9  738.15   216.4  737.41   255.7  733.78     295  732.57
   314.7  730.64   363.9  722.72   403.2  720.22   461.2  712.83   470.6  710.35
   489.2  702.69   498.5  700.32   507.9   700.8   517.2  704.84   526.5  709.31
   545.2  712.48   563.8  713.52   612.3  713.13   631.9  714.34   641.6  716.02
   700.4  734.92   768.9  754.35   798.2  761.84   827.6  767.29   886.3   774.6
   896.1   776.6     945  791.29   974.4  797.97  1003.7  800.98  1033.1  800.57
#Mann= 3 , 0 , 0
       0     .05       0   489.2    .045       0   517.2     .06       0
Bank Sta=489.2,517.2
XS Rating Curve= 0 ,0
Exp/Cntr=0.3,0.1

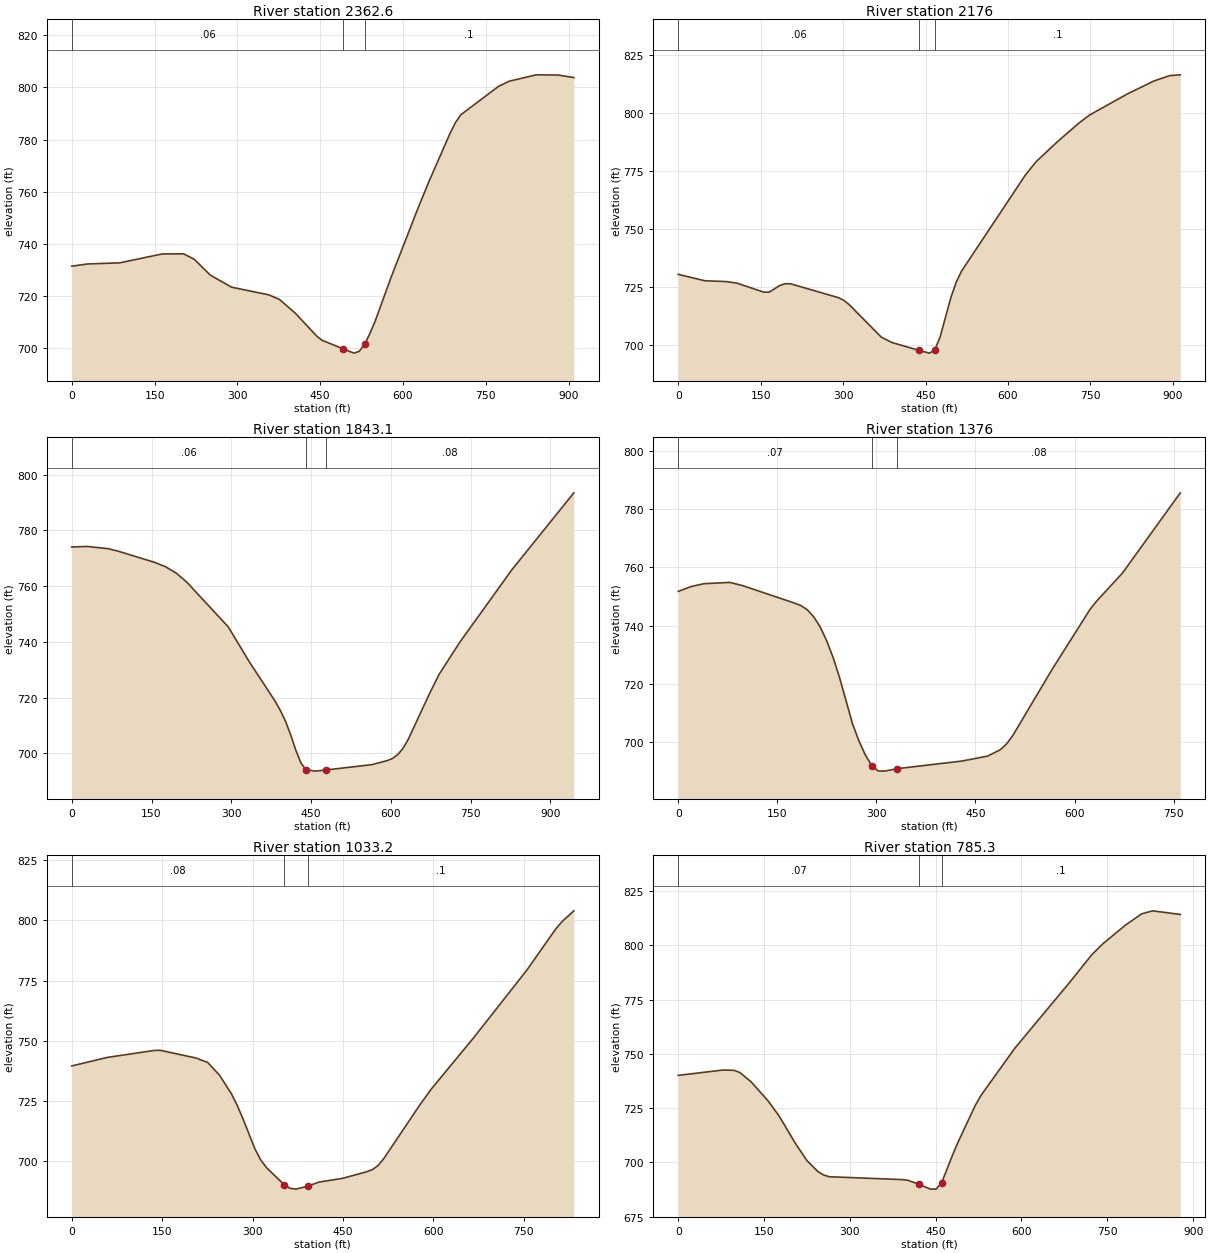
Type RM Length L Ch R = 1 ,2362.6  ,181.7,186.6,191.6
XS GIS Cut Line= 4
     1871327.926      674298.763     1871185.565      673878.624
      1871147.37      673729.319     1871095.287      673422.027
#Sta/Elev= 30
       0  731.48    28.9  732.32    86.8  732.75   163.9  736.16   202.5   736.2
   221.8  734.14   250.7  728.08   289.3  723.43   356.8  720.49   376.1  718.74
     405  713.44   443.6   704.7   453.2  703.09   491.8   699.8     511  698.15
   520.7  698.83   530.3  701.49   539.9   705.6   549.6  710.44   578.4  727.22
   626.9  753.57   646.4  763.63   685.4  782.47   695.1  786.55   704.8  789.51
     773  800.37   792.5  802.35   841.2  804.79   880.2  804.72   909.4  803.75
#Mann= 3 , 0 , 0
       0     .06       0   491.8    .045       0   530.3      .1       0
Bank Sta=491.8,530.3
XS Rating Curve= 0 ,0
Exp/Cntr=0.3,0.1

Type RM Length L Ch R = 1 ,2176    ,339.3,332.9,325.8
XS GIS Cut Line= 3
     1871378.201      674294.591     1871353.825      673838.025
      1871338.58      673381.917
#Sta/Elev= 30
       0  730.32    48.6  727.54    87.6  727.19     107  726.51   155.6  722.62
   165.4  722.63   184.8  725.49   194.6  726.28   204.3  726.25   291.8  720.22
   301.6  719.06   311.3  717.18   369.7  703.15   389.1  700.85   437.8  697.49
   457.2  696.28   466.9  697.73   476.6   703.3   496.1   720.3   505.8  726.91
   515.5   731.7     632  773.33   651.4  779.03   690.2  787.68   729.1  795.67
   748.5  799.16   816.5  808.16     865   813.8   894.2  816.18   913.6  816.52
#Mann= 3 , 0 , 0
       0     .06       0   437.8    .045       0   466.9      .1       0
Bank Sta=437.8,466.9
XS Rating Curve= 0 ,0
Exp/Cntr=0.3,0.1

Type RM Length L Ch R = 1 ,1843.1  ,482.3,467.1,451.9
XS GIS Cut Line= 4
     1871836.606      674260.569     1871695.981      673873.416
     1871664.731      673784.874      1871537.95      673365.514
#Sta/Elev= 30
       0  774.08    29.4  774.26    68.6  773.46    88.3  772.51   156.9  768.48
   176.5  766.96   196.1  764.72   215.8  761.52   294.2  745.39   333.4  732.95
   382.5  718.63   392.3  715.29   402.1  711.38   411.9  706.44   421.3  701.05
   430.7  696.55   440.1  694.08   457.2  693.57   477.6  693.98   564.2   695.9
   593.4  697.37   603.2  698.15   612.9  699.51   622.6  701.73   632.4   704.9
   671.3   720.9   690.8  728.39   729.7  739.92   827.1  765.82   943.9  793.52
#Mann= 3 , 0 , 0
       0     .06       0   440.1    .045       0   477.6     .08       0
Bank Sta=440.1,477.6
XS Rating Curve= 0 ,0
Exp/Cntr=0.3,0.1

Type RM Length L Ch R = 1 ,1376    ,343.7,342.8,342.6
XS GIS Cut Line= 3
     1872275.842      673680.708     1872019.198      673520.139
     1871631.988      673276.559
#Sta/Elev= 30
       0  751.73    19.5  753.39    39.1  754.38    78.1  754.81    97.7   753.7
   175.8  747.73   185.6  746.88   195.3  745.44   205.1  743.01   214.8  739.58
   224.6  734.87   234.4  729.09   244.1  722.27   263.7   706.4   273.4  700.46
   283.2   695.6     293   691.9   302.7  690.07   312.5     690   331.9  690.85
   429.3  693.45   468.2  695.15   487.7  697.36   497.4  699.41   507.1  702.41
   565.5  724.73   623.9  745.68   633.7  748.44   672.6  758.02   760.2  785.58
#Mann= 3 , 0 , 0
       0     .07       0     293    .045       0   331.9     .08       0
Bank Sta=293,331.9
XS Rating Curve= 0 ,0
Exp/Cntr=0.3,0.1

Type RM Length L Ch R = 1 ,1033.2  ,233.8,247.9,260
XS GIS Cut Line= 4
     1872425.148      673482.791     1872211.606      673239.736
     1872128.273      673191.124     1871732.143      673074.617
#Sta/Elev= 30
       0  739.57    58.8  743.11   137.3  746.03   147.1  746.05   205.9  742.87
   225.5  741.03   245.1  735.73   264.7  728.09   274.5  723.17   284.3  717.45
   303.9  705.11   313.7  700.46   323.5  697.24   352.5  690.23   362.1  688.78
   371.8  688.43   391.1  689.64   410.4  691.37   449.5  692.92   488.8  695.62
   498.7  696.52   508.5  698.29   518.3  701.36   577.3  723.35     597  730.15
   665.8  751.01   754.3  779.15   803.4  796.61   813.3   799.5   832.9  803.97
#Mann= 3 , 0 , 0
       0     .08       0   352.5    .045       0   391.1      .1       0
Bank Sta=352.5,391.1
XS Rating Curve= 0 ,0
Exp/Cntr=0.3,0.1

Type RM Length L Ch R = 1 ,785.3   ,229.8,236.9,243.3
XS GIS Cut Line= 4
      1872459.87      673397.722     1872312.301       673121.68
     1872199.453      672892.513     1872032.787      672632.097
#Sta/Elev= 30
       0  740.12    78.2  742.57    97.8  742.43   107.6  741.45   127.2  737.19
   156.5  728.54   176.1  721.49   205.4  708.53     225  700.82   244.5  695.71
   254.3  694.18   264.1  693.39   391.6  692.07   401.4  691.75   421.1   689.9
   440.7  687.69   450.6  687.68   460.4  690.62     480  703.75   489.9   709.8
   519.3  726.33   529.2  730.86   587.8  752.45   684.4  783.06     723  795.77
   742.4   800.8     781  809.23     810  814.57   829.3  815.96   877.6  814.29
#Mann= 3 , 0 , 0
       0     .07       0   421.1    .045       0   460.4      .1       0
Bank Sta=421.1,460.4
XS Rating Curve= 0 ,0
Exp/Cntr=0.3,0.1

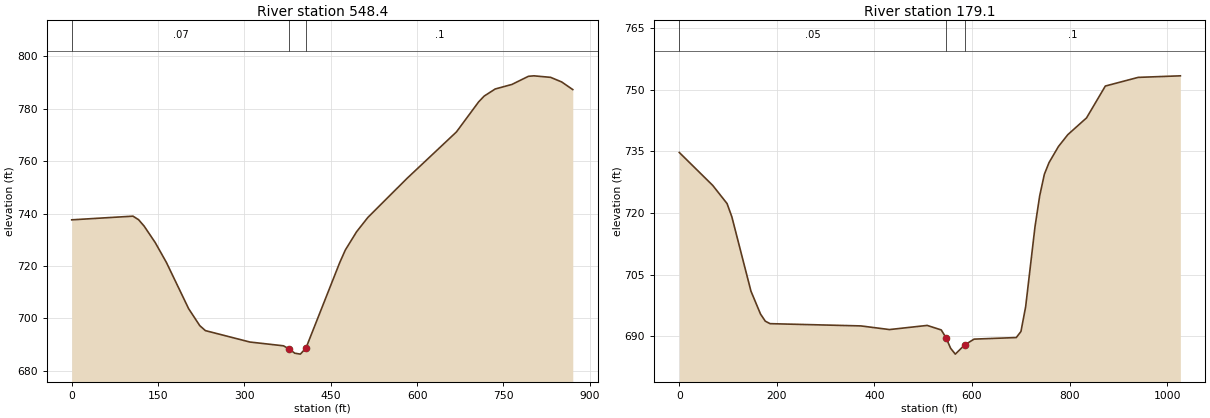
Type RM Length L Ch R = 1 ,548.4   ,370.5,369.3,368.7
XS GIS Cut Line= 4
     1872502.839      673408.572     1872501.103      673070.031
     1872473.325       672896.42     1872218.117      672648.156
#Sta/Elev= 30
       0  737.59   106.4  738.99   116.1  737.65   125.8   735.2   145.1  728.91
   164.4  721.39   203.1  703.74   222.5  697.26   232.2  695.38   309.5  691.03
   367.8  689.59   377.6  688.41   387.4  686.78   397.2  686.42   406.9  688.72
   465.5  721.26   475.3  726.09   494.8  733.03   514.4  738.49   581.7  753.22
   668.3  771.08   706.8  782.51   716.4  784.73   735.7  787.45   764.6  789.17
   793.4  792.28     803  792.46   831.9  791.88   851.2  790.12   870.4  787.22
#Mann= 3 , 0 , 0
       0     .07       0   377.6    .045       0   406.9      .1       0
Bank Sta=377.6,406.9
XS Rating Curve= 0 ,0
Exp/Cntr=0.3,0.1

Type RM Length L Ch R = 1 ,179.1   ,190.2,179.1,167.8
XS GIS Cut Line= 4
     1872539.297      673387.739      1872881.97      673095.313
     1872836.172      672879.058     1872504.575      672750.586
#Sta/Elev= 30
       0  734.76    68.6  726.72    97.9   722.3   107.7  719.08   146.9  700.94
   166.5  695.36   176.3  693.62   186.1  693.02   372.1  692.47   430.9  691.58
   508.2  692.59     537  691.49   546.6  689.63   556.2  687.02   565.8  685.59
     585  687.83   604.3  689.25   690.8  689.63   700.4  691.11     710  697.12
   729.2  716.66   738.8  724.18   748.4  729.45     758   732.3   777.3  736.22
   796.5  739.11   834.9   743.2   873.4  750.96   940.6  753.07  1027.2  753.45
#Mann= 3 , 0 , 0
       0     .05       0   546.6    .045       0     585      .1       0
Bank Sta=546.6,585
XS Rating Curve= 0 ,0
Exp/Cntr=0.3,0.1

Chan Stop Cuts=-1
Use User Specified Reach Order=0
Composite Channel Slope=5